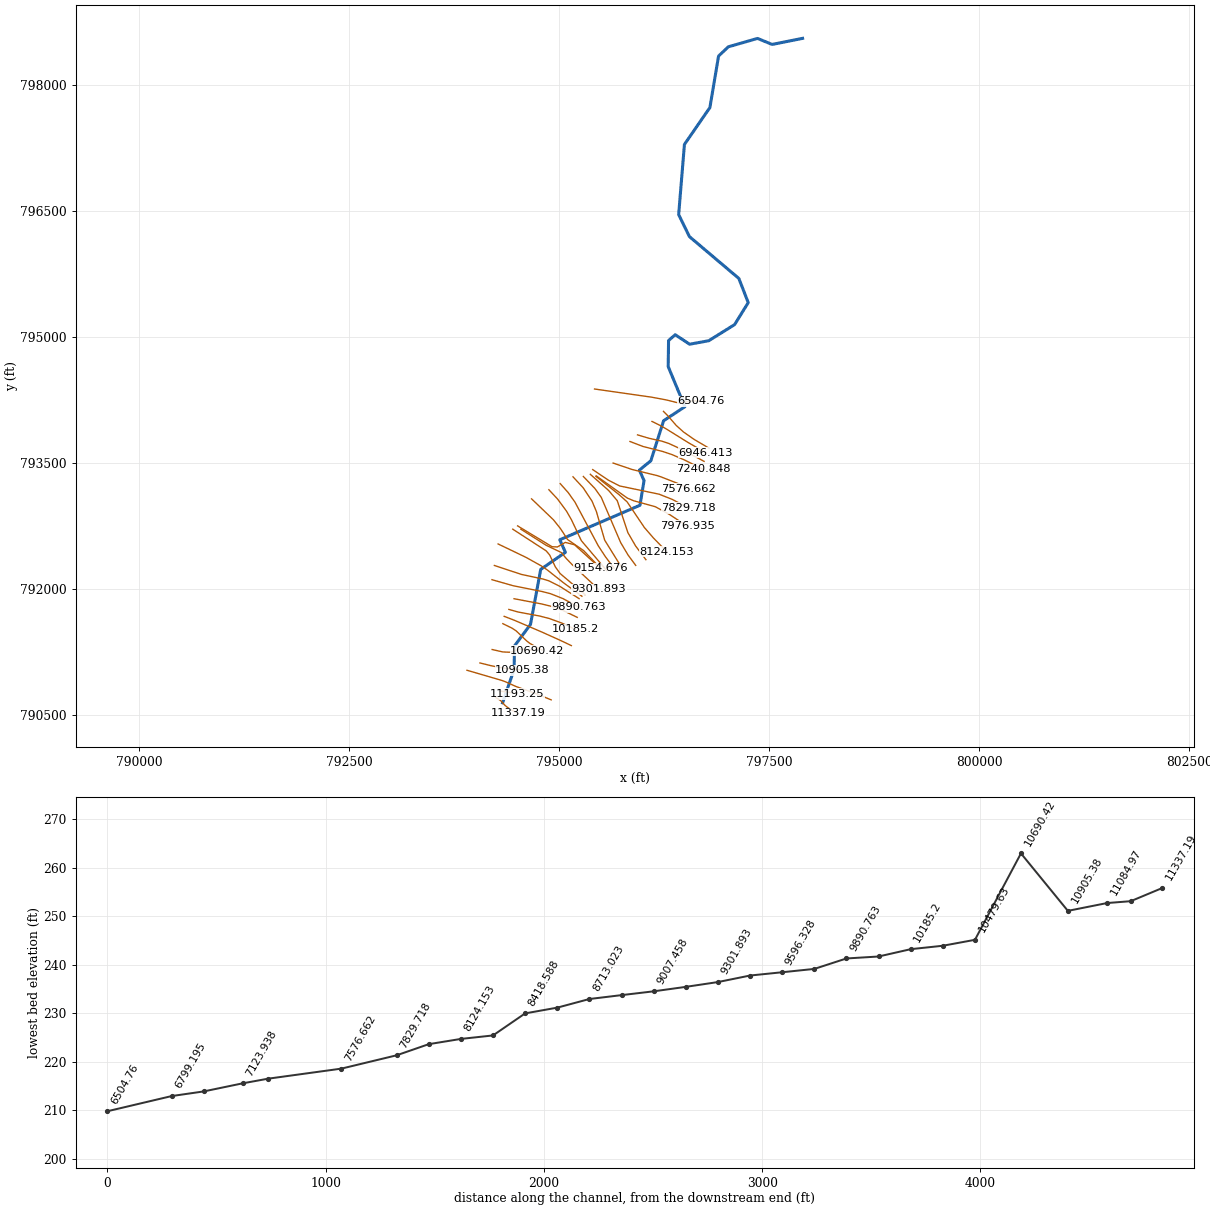
--- 17588_ras.prj (project) ---

Proj Title=17588
Current Plan=p01
Default Exp/Contr=0.3,0.1
English Units
Geom File=g01
Flow File=f01
Plan File=p01
Y Axis Title=Elevation
X Axis Title(PF)=Main Channel Distance
X Axis Title(XS)=Station
BEGIN DESCRIPTION:
RFD model 17588 exported to HEC-RAS
END DESCRIPTION:

--- 17588_ras.p01 (plan) ---

Plan Title=Plan 01
Program Version=4.10
Short Identifier=Plan 01
Geom File=g01
Flow File=f01
Subcritical Flow
Calc Critical at every XS
Secant Critical Depth

--- 17588_ras.f01 (steady flow) ---

Flow Title=Flow 01
Program Version=5.01
Number of Profiles= 6
Profile Names=10yr,25yr,50yr,100yr,100plus,500yr
River Rch & RM=17588,37,11337.19
 1093.68 1776.52 2425.96 3023.38 4414.13 5953.86
River Rch & RM=17588,37,11193.25
 1094.43 1777.76 2427.68 3025.54 4417.29 5957.62
River Rch & RM=17588,37,11084.97
 1110.35 1804.05 2463.99  3071.2 4483.95  6036.4
River Rch & RM=17588,37,10905.38
 1112.58 1807.76 2469.12 3077.67  4493.4 6047.62
River Rch & RM=17588,37,10690.42
 1116.55 1814.34 2478.24 3089.16 4510.18 6067.55
River Rch & RM=17588,37,10479.63
 1119.53 1819.27 2485.07 3097.78 4522.75 6082.48
River Rch & RM=17588,37,10332.42
 1139.85 1852.74 2531.22  3155.7 4607.32 6181.64
River Rch & RM=17588,37, 10185.2
 1140.84 1854.38 2533.48 3158.55 4611.49 6186.58
River Rch & RM=17588,37,10037.98
 1142.56 1857.23 2537.44 3163.55 4618.78 6195.23
River Rch & RM=17588,37,9890.763
 1144.47 1860.43  2541.9  3169.2 4627.03  6205.1
River Rch & RM=17588,37,9743.546
 1145.43 1862.03 2544.13 3172.02 4631.15 6210.04
River Rch & RM=17588,37,9596.328
 1248.65 2034.29 2783.69 3475.05 5073.57 6734.33
River Rch & RM=17588,37,9449.111
 1250.28 2037.03 2787.51 3479.89 5080.64 6742.69
River Rch & RM=17588,37,9301.893
 1252.15 2040.16 2791.88 3485.42 5088.72 6752.24
River Rch & RM=17588,37,9154.676
 1260.04 2053.29  2810.1 3508.43 5122.31 6791.58
River Rch & RM=17588,37,9007.458
 1261.45 2055.64 2813.37 3512.58 5128.36 6798.72
River Rch & RM=17588,37,8860.241
 1263.81 2059.59 2818.86 3519.52  5138.5 6810.62
River Rch & RM=17588,37,8713.023
 1268.57 2067.51 2829.87 3533.42 5158.79  6834.4
River Rch & RM=17588,37,8565.806
 1316.15 2145.88 2937.98 3669.16 5356.97 7062.17
River Rch & RM=17588,37,8418.588
 1321.86 2155.37 2951.13 3685.76 5381.21  7090.3
River Rch & RM=17588,37,8271.371
    1324 2158.92 2956.07 3691.98 5390.29 7100.83
River Rch & RM=17588,37,7976.935
 1327.33 2164.46 2963.74 3701.66 5404.42 7117.21
River Rch & RM=17588,37,7829.718
 1329.71 2168.41 2969.22 3708.57 5414.51 7128.89
River Rch & RM=17588,37,7576.662
 1334.36 2176.19 2980.04 3722.27 5434.51 7152.25
River Rch & RM=17588,37,7240.848
  1338.3 2182.77 2989.21 3733.88 5451.47 7172.07
River Rch & RM=17588,37,7123.938
 1339.23 2184.32 2991.37 3736.62 5455.46 7176.73
River Rch & RM=17588,37,6946.413
 1341.08 2187.41 2995.68 3742.08 5463.44 7186.05
River Rch & RM=17588,37,6799.195
 1341.77 2188.57  2997.3 3744.13 5466.42 7189.55
River Rch & RM=17588,37, 6504.76
 1345.24 2194.38 3005.38 3754.36 5481.37    7207
River Rch & RM=17588,37,6341.304
  1586.1 2589.47 3548.98 4435.12 6475.27 8321.25
River Rch & RM=17588,37,6210.325
 1587.66 2592.09 3552.62 4439.74 6482.01 8328.94
River Rch & RM=17588,37,6063.107
 1590.58 2596.95  3559.4 4448.32 6494.55 8343.22
River Rch & RM=17588,37,5768.672
 1614.26 2636.66 3614.81  4518.6 6597.15 8460.43
River Rch & RM=17588,37,5272.781
 1617.34 2641.84 3622.04 4527.76 6610.53 8475.71
Boundary for River Rch & Prof#=17588,37,1
Up Type= 0
Dn Type= 2
Boundary for River Rch & Prof#=17588,37,2
Up Type= 0
Dn Type= 2
Boundary for River Rch & Prof#=17588,37,2
Up Type= 0
Dn Type= 2
Boundary for River Rch & Prof#=17588,37,2
Up Type= 0
Dn Type= 2
Boundary for River Rch & Prof#=17588,37,2
Up Type= 0
Dn Type= 2
Boundary for River Rch & Prof#=17588,37,2
Up Type= 0
Dn Type= 2

--- 17588_ras.g01 (geometry) ---

Geom Title=17588
Program Version=4.10

River Reach=17588,37
Reach XY= 30
 794328.24558592790644.813810552794465.392468691791044.436114883
794470.403326542791322.655593377794660.220922681 791578.78981745
794781.966123911 792233.46979891795075.815337212792436.658275536
795009.068155529792585.825709923795963.406990859792996.978412253
 796011.80811897793291.352608269795955.621454747793414.727301604
796092.688284964793526.146813537796244.440217556794002.702984561
796497.899617733794169.592047108796299.377633723794647.057044539
796303.588181766794957.446548711796382.791098595795026.473627501
796554.502816233794913.469231797796782.279791089794955.231539765
797089.662779481795146.924591253 797251.98004499795408.832756773
797140.365537734795696.437323707796551.901426646796194.666696933
796423.933236423796456.562513493796492.484515937797291.840479751
796795.670148371797730.739218687796898.974754245798344.126544131
797015.368884593798453.810915056797361.978177131798553.584497686
797536.786148757798482.159630337797898.974410029798554.617966289

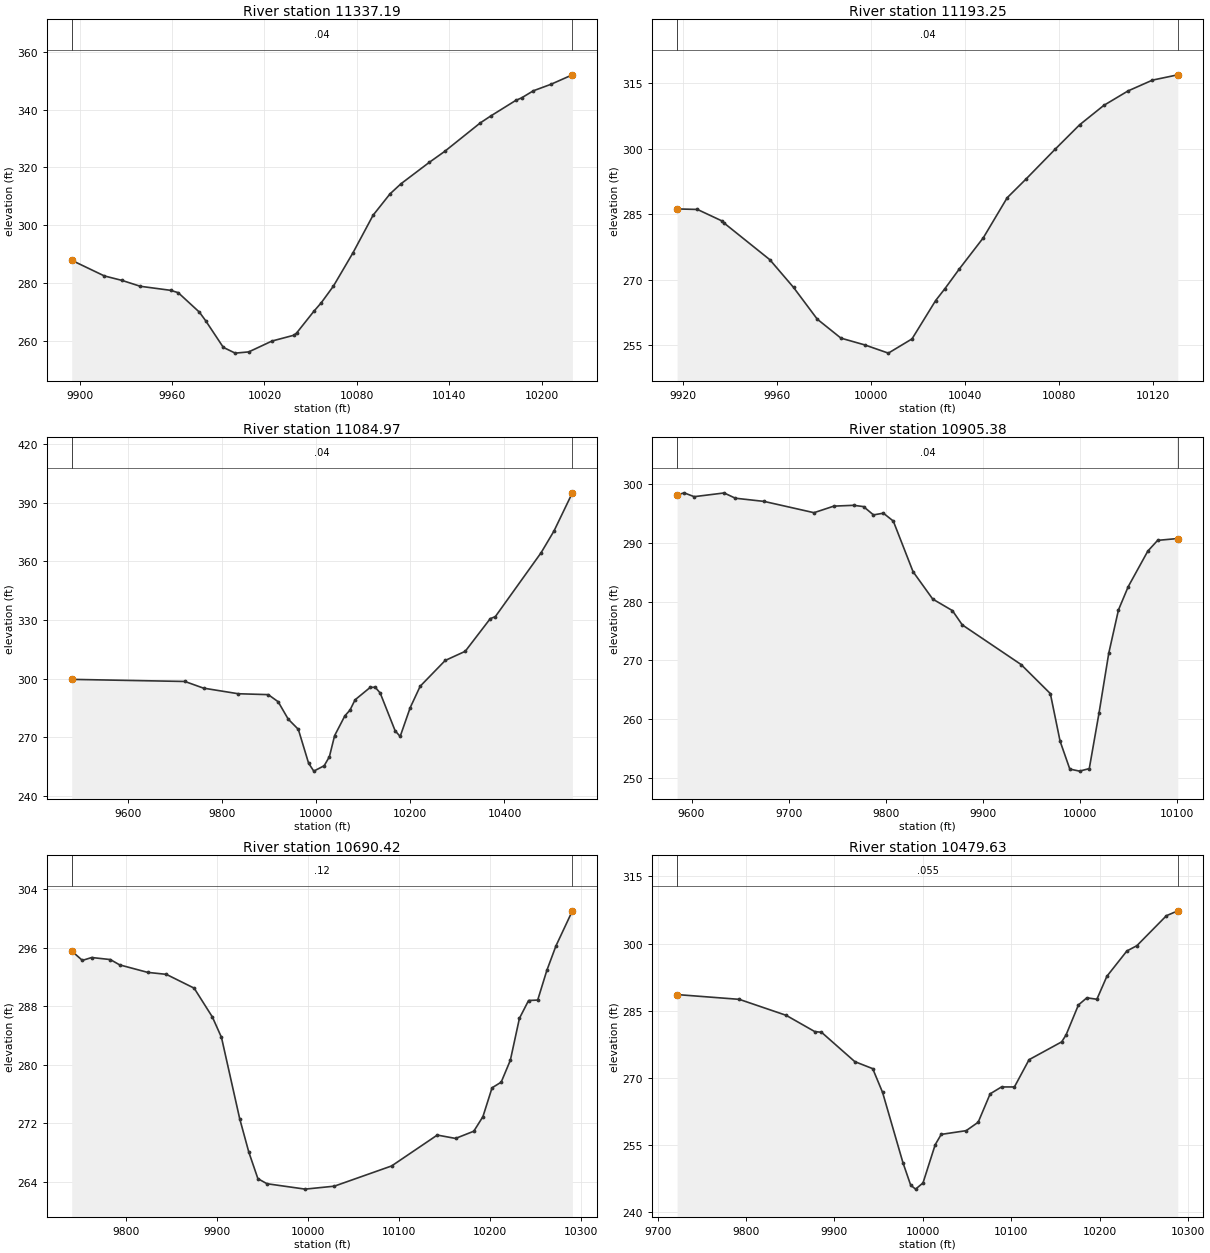
Type RM Length L Ch R = 1 ,11337.19,143.938000,143.938000,143.938000
XS GIS Cut Line= 6
794246.219352901790708.139716274794303.668515392790673.223048683
794356.564529005  790614.6619276794385.504301949 790591.80495395
794423.498376585790566.763400021794507.342603182790519.411508829
#Sta/Elev= 30
9894.834287.91669916.063282.51069927.539280.96389939.358278.94049959.103 277.536
9964.023276.72159977.788269.98339981.828267.04229993.295257.8258   10001255.8332
10009.82256.259210024.92260.014110039.09262.013210040.83262.742110052.06270.2689
 10056.9273.2385 10064.8278.995210077.54290.545110090.55303.491710101.53310.8596
10108.72314.390310127.18321.819210137.01325.537810160.17335.404310166.83337.7532
10183.26 343.19510187.11344.088310194.62346.504910205.98348.734510219.99 352.026
#Mann= 3 , 0 , 0
9894.834    0.04       09894.834    0.04       010219.99    0.04       0
#XS Ineff= 2 , 0
       0                               0
Bank Sta=9894.834,10219.99
Exp/Cntr=0.3,0.1

Type RM Length L Ch R = 1 ,11193.25,108.286200,108.286200,108.286200
XS GIS Cut Line= 6
794286.582966103 790789.61889739794322.919030264790781.054066675
794398.918050801 790772.04008243794432.807432042790766.216096722
794478.527059618790754.975052951794495.279708152790749.812803479
#Sta/Elev= 23
9917.578286.19389926.225286.07299936.499283.4785 9937.71282.88729957.007274.5472
9967.085268.19389977.164260.91779987.242256.56299997.321255.018410007.39253.1281
10017.45256.3917 10027.5 265.18910031.44267.910310037.62272.470210047.76279.5761
10057.91288.759210065.83292.995610078.39299.930910088.68305.469910098.98309.9285
10109.28313.246910119.69315.729910130.44316.9414
#Mann= 3 , 0 , 0
9917.578    0.04       09917.578    0.04       010130.44    0.04       0
#XS Ineff= 2 , 0
       0                               0
Bank Sta=9917.578,10130.44
Exp/Cntr=0.3,0.1

Type RM Length L Ch R = 1 ,11084.97,179.589800,179.589800,179.589800
XS GIS Cut Line= 6
793903.937158348791032.827171565794321.983666959790910.590932161
794373.295971231790890.728685653794484.010816367790840.791148121
794744.306254332790746.593493665794906.584261077790680.203347236
#Sta/Elev= 30
9480.103299.67639720.718298.59989760.281295.19179834.063292.32439897.869291.8687
9918.919288.24729940.365 279.3329961.811274.11869983.617256.82949994.648252.7454
10016.76255.498110027.85260.117710038.94270.894410060.73281.020810071.57 283.932
10082.42289.214310114.51295.552210125.15295.674110135.78292.716610167.69273.3318
10178.32270.491610199.59285.192210220.86296.175410274.03309.343910316.57314.0243
10369.76330.724610380.56331.7684 10477.8 364.43310505.26375.564710544.34 395.083
#Mann= 3 , 0 , 0
9480.103    0.04       09480.103    0.04       010544.34    0.04       0
#XS Ineff= 2 , 0
       0                10081.82       0
Bank Sta=9480.103,10544.34
Exp/Cntr=0.3,0.1

Type RM Length L Ch R = 1 ,10905.38,214.957700,214.957700,214.957700
XS GIS Cut Line= 6
794058.064480475791119.636376055794188.165415417791087.525231242
794286.004205451791067.467083117 794369.64872301791053.697994799
794505.600809068791042.305412814794565.507741111791034.038442118
#Sta/Elev= 30
9585.172298.13069592.363 298.5069602.727 297.8519633.599298.48459645.162297.5896
9674.763297.04519726.161295.12389746.576296.24189766.992296.3813  9777.2296.1601
9787.408294.74919797.616295.04099807.824293.70229828.174285.08499848.444280.4209
9868.713 278.4589878.847276.03179939.418269.28089969.584264.33029979.603256.2382
9989.623251.48329999.645251.132610009.67 251.56210019.69260.990410029.72271.1848
10039.74278.575210049.82 282.54610069.99288.594910080.07 290.41310100.83290.7264
#Mann= 3 , 0 , 0
9585.172    0.04       09585.172    0.04       010100.83    0.04       0
#XS Ineff= 2 , 0
       0                               0
Bank Sta=9585.172,10100.83
Exp/Cntr=0.3,0.1

Type RM Length L Ch R = 1 ,10690.42,210.786500,210.786500,210.786500
XS GIS Cut Line= 6
794203.552200764791279.403954655794329.359989941791250.967947528
794399.157462031791247.521158785794426.731771946791247.521158785
794526.688645542791285.435834959794742.974639326791266.478496864
#Sta/Elev= 30
9740.511295.56799752.248294.2826  9762.5 294.6779783.004294.39769793.257 293.669
9824.014292.64529844.518292.37569875.139290.48579895.164286.54159905.176283.7483
  9925.2272.62859935.213268.06049945.218264.41879955.218263.72539997.183262.9867
10029.27 263.39110092.24266.158510142.43270.384210162.51 269.92410182.58  270.91
10192.62272.905210202.66276.8504 10212.7277.624510222.74280.612110232.77 286.363
10242.81288.795410252.85288.856210262.89292.914910272.93296.270810290.97301.0657
#Mann= 3 , 0 , 0
9740.511    0.12       09740.511    0.12       010290.97    0.12       0
#XS Ineff= 2 , 0
       0                               0
Bank Sta=9740.511,10290.97
Exp/Cntr=0.3,0.1

Type RM Length L Ch R = 1 ,10479.63,147.217500,147.217500,147.217500
XS GIS Cut Line= 6
794331.097956158 791587.23376708794441.752997052791532.998238395
794490.099905006791500.690494013794617.851352907791379.188343516
 794656.31193391791350.141644627794796.599649866791273.225149218
#Sta/Elev= 30
9721.998288.60899792.318287.54359845.328283.97799877.722280.34049885.316 280.193
9922.997273.63269943.243272.06499954.429266.7414 9977.39251.09479986.196246.0403
9991.733 245.15910000.12246.5445 10013.9255.0696 10020.7257.382210048.96258.2177
10062.52260.096610076.09266.447410088.92267.9798 10103.5267.978610120.09274.0713
10156.92 278.04310161.89279.577410175.92286.292910185.42287.888210196.79287.5633
 10208.1292.694410230.71 298.34510242.01299.526610275.42306.222710288.29307.3131
#Mann= 3 , 0 , 0
9721.998   0.055       09721.998   0.055       010288.29   0.055       0
#XS Ineff= 2 , 0
       0                               0
Bank Sta=9721.998,10288.29
Exp/Cntr=0.3,0.1

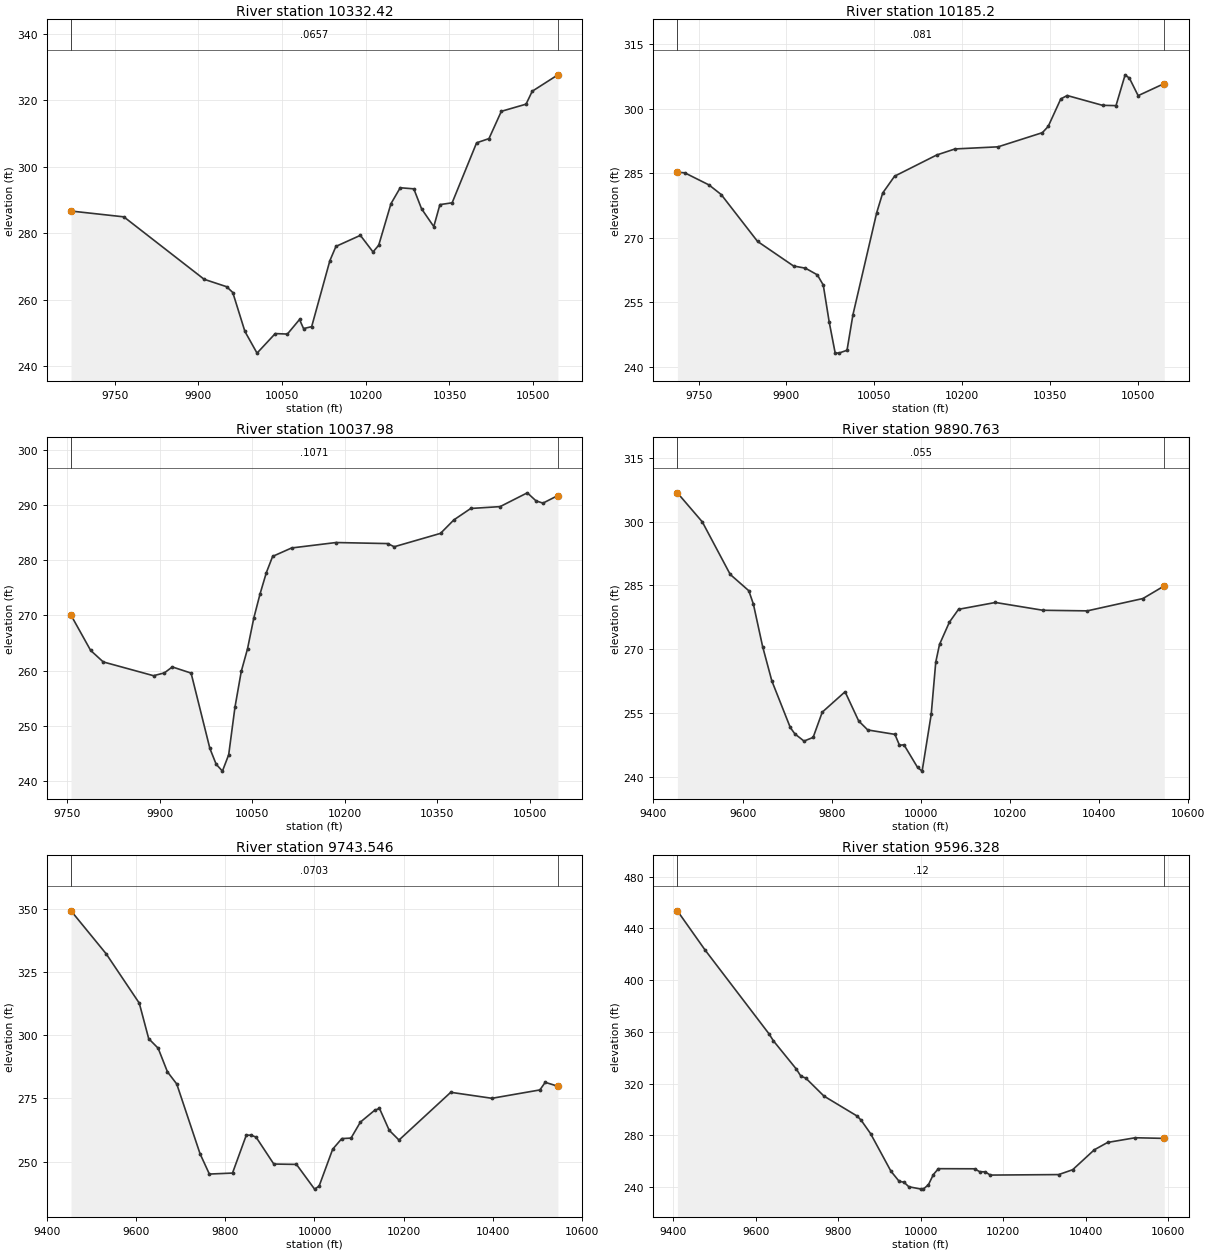
Type RM Length L Ch R = 1 ,10332.42,147.217600,147.217600,147.217600
XS GIS Cut Line= 6
794346.667072654791674.680337329794463.816013535791629.389321697
794651.271455408791549.428099497794791.963540372791489.163628638
795014.430235312791389.070000425 795146.58512716 791326.12308968
#Sta/Elev= 30
9671.603286.65179766.308284.90289910.312266.12819950.701263.89579961.573262.1542
9983.318250.454610005.06243.934910037.69249.812110059.45249.666810081.21254.0485
10088.44251.311510102.97251.8938 10135.6271.735410146.48276.023510190.28279.3419
10212.95274.352310223.18276.383910245.11 288.86310261.69293.651410286.06293.3252
10299.94287.333310321.87281.971310332.83  288.5810354.77289.125510398.63307.1618
10420.79308.428910442.94316.630510487.25318.780810498.32322.665410544.38327.5999
#Mann= 3 , 0 , 0
9671.603  0.0657       09671.603  0.0657       010544.38  0.0657       0
#XS Ineff= 2 , 0
       0                10039.63       0
Bank Sta=9671.603,10544.38
Exp/Cntr=0.3,0.1

Type RM Length L Ch R = 1 , 10185.2,147.217500,147.217500,147.217500
XS GIS Cut Line= 6
794402.944456624791756.664674457794514.631440843791725.585910904
794768.318993578791678.344557328794882.542228928791649.026602798
795031.083498547   791595.218998795195.165955473791519.089760717
#Sta/Elev= 30
  9713.8285.23939726.314285.12219767.834282.29799788.593 280.0699850.591 269.187
 9912.04263.47179932.388262.96089952.649261.4134 9962.78259.04369972.911250.4417
9983.042243.2914 9989.27243.2267 10003.3243.890710013.45252.168410054.05275.8984
10064.19 280.42310084.49284.335110156.46289.2661 10187.6290.665610261.08291.1583
10336.69294.446410346.61 295.89410368.12302.287410379.04 303.07910439.35300.8023
10462.36300.729310477.92307.8858 10485.3307.097510500.14303.046510544.77305.8639
#Mann= 3 , 0 , 0
  9713.8   0.081       0  9713.8   0.081       010544.77   0.081       0
#XS Ineff= 2 , 0
       0                               0
Bank Sta=9713.8,10544.77
Exp/Cntr=0.3,0.1

Type RM Length L Ch R = 1 ,10037.98,147.217600,147.217600,147.217600
XS GIS Cut Line= 6
794463.865090002791884.340254467794789.802163248791822.626149443
794904.357601488791794.588754763 794968.94808245791773.991584199
795053.139804593791741.536572298 795216.61965969791662.500583159
#Sta/Elev= 30
9756.114 270.0589787.913263.6581 9808.34261.56339889.868259.0588 9907.46259.5677
9920.331260.65129950.795 259.5329981.258245.83179991.412242.975910001.58241.7163
10011.75244.697710021.93253.3413 10032.1259.822610042.28263.949510052.46269.5367
10062.63273.940910072.81277.798710082.98280.7419 10113.7282.272110185.78283.2611
10269.48  283.0710280.11282.495210355.13 284.92410376.86287.378910404.19289.4509
10451.73289.786610495.85292.293110510.02290.832610521.23290.421610545.49 291.803
#Mann= 3 , 0 , 0
9756.114  0.1071       09756.114  0.1071       010545.49  0.1071       0
#XS Ineff= 2 , 0
       0                               0
Bank Sta=9756.114,10545.49
Exp/Cntr=0.3,0.1

Type RM Length L Ch R = 1 ,9890.763,147.217500,147.217500,147.217500
XS GIS Cut Line= 6
794201.463939965792110.690472517794456.785125211792038.118202668
794797.148072192791970.175361253794897.846757602 791944.24066986
795047.132341232791885.362629403795236.489758436791782.756693578
#Sta/Elev= 30
9453.672306.78889509.589299.95289572.257287.59099613.905283.75629624.245280.6053
9644.925270.63149665.604262.54539706.963251.58779717.303250.0723  9737.8 248.382
9758.279249.24449778.758255.18649829.956259.98269860.498253.11919880.834250.9982
9941.844  249.969952.013 247.4049962.181247.50049992.686242.176610002.87241.3109
10023.27254.669110033.47266.967110041.89271.118910064.08276.3647 10084.6279.3809
10167.32 280.99110274.01279.156710373.38279.017610498.44281.921410546.29284.8987
#Mann= 3 , 0 , 0
9453.672   0.055       09453.672   0.055       010546.29   0.055       0
#XS Ineff= 2 , 0
       09804.543                       0
Bank Sta=9453.672,10546.29
Exp/Cntr=0.3,0.1

Type RM Length L Ch R = 1 ,9743.546,147.217600,147.217600,147.217600
XS GIS Cut Line= 6
794230.237477371792279.859372617794552.807026347792173.304674824
794808.761088801792118.651677506794878.704002612792097.092726719
795008.606640266792032.004360508795238.860405067 791885.18604777
#Sta/Elev= 30
9453.294349.19969532.463332.15549606.588312.69429627.767298.63759648.936294.8832
9669.854285.52269690.771280.71559743.066253.13479763.984245.1131 9815.94245.5029
9846.859260.47699857.165260.49139868.709259.74959908.697 249.0729959.591248.9306
10000.23239.1538 10010.4240.342410040.92254.957810061.38259.142410082.08259.3308
 10103.1265.658410135.04 270.31210145.97271.076810167.83262.426410189.79 258.557
10306.01277.438110398.54275.072310506.19278.378910518.15281.386610546.68279.8289
#Mann= 3 , 0 , 0
9453.294  0.0703       09453.294  0.0703       010546.68  0.0703       0
#XS Ineff= 2 , 0
       09858.659                       0
Bank Sta=9453.294,10546.68
Exp/Cntr=0.3,0.1

Type RM Length L Ch R = 1 ,9596.328,147.217500,147.217500,147.217500
XS GIS Cut Line= 6
794274.568357604792536.100382785794606.791413907792376.456952237
 794788.20022297792275.388124026794859.958310527792226.762843313
795055.820516055792071.873099326795272.031141737791914.010098711
#Sta/Elev= 30
9409.786453.64899476.669423.46029631.614 358.6619642.681353.09859698.349331.2247
9709.498325.60679720.646324.43149765.239310.38659845.634294.95239855.557291.6298
9878.185281.36059927.485252.34199947.278244.55479959.212243.7942  9970.8240.3171
   10001238.466310006.23238.563710018.34241.846910030.45249.764510042.56 254.277
 10130.2254.187910142.95251.8982 10155.7251.844910168.45249.328810334.14249.7107
10368.06253.471410420.52  268.8810452.85274.571210519.58278.192710590.19277.6951
#Mann= 3 , 0 , 0
9409.786    0.12       09409.786    0.12       010590.19    0.12       0
#XS Ineff= 2 , 0
       0                10075.33       0
Bank Sta=9409.786,10590.19
Exp/Cntr=0.3,0.1

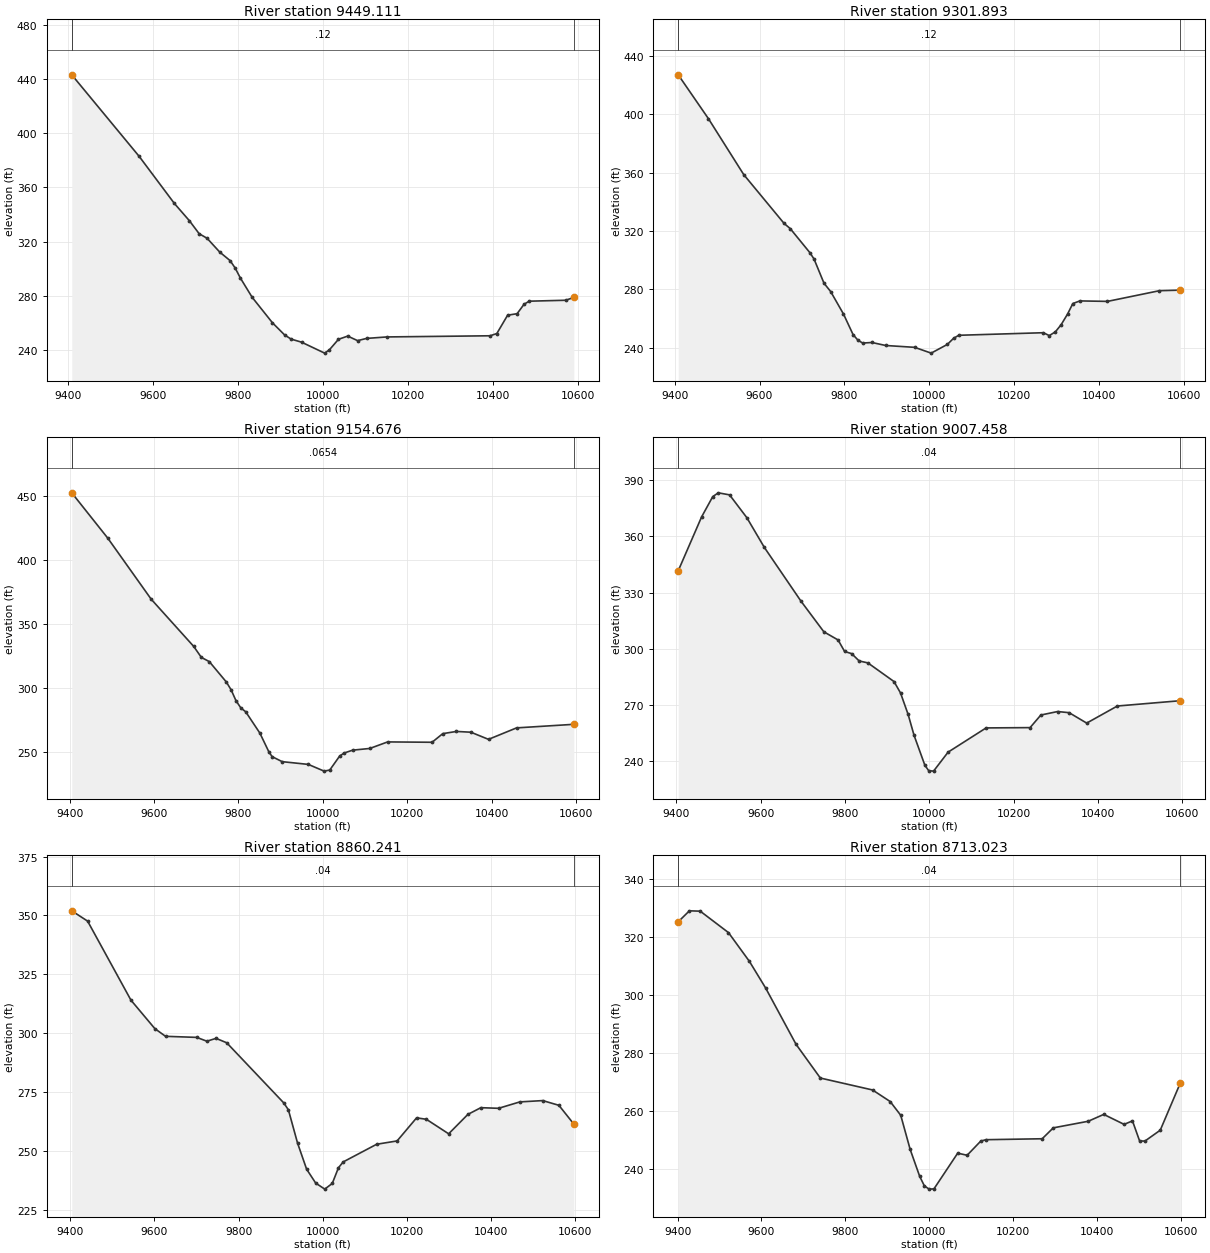
Type RM Length L Ch R = 1 ,9449.111,147.217600,147.217600,147.217600
XS GIS Cut Line= 6
794449.042283597792712.140966708 794846.98662717792453.632117361
794889.459600391 792403.52733445794956.110535813792262.502948166
795013.788272993792183.180723018795308.074254635 791933.37936255
#Sta/Elev= 30
9409.191443.07829568.008382.84929650.637348.20369686.123335.41749708.963325.8843
9727.685322.50169757.542 312.2919781.703306.06819793.784300.55449805.864293.2632
9833.759278.95279881.598260.1363 9910.01251.24219925.325248.14439949.981245.8735
10004.32237.789510015.17240.109810036.87247.980110058.56250.350810081.86247.0039
10103.29248.654210150.86249.733810393.71250.585110409.58252.242810434.98265.7762
10457.31266.879710473.66273.842410485.86 276.10610571.82276.793310590.83278.9003
#Mann= 3 , 0 , 0
9409.191    0.12       09409.191    0.12       010590.83    0.12       0
#XS Ineff= 2 , 0
       09953.659        10058.29       0
Bank Sta=9409.191,10590.83
Exp/Cntr=0.3,0.1

Type RM Length L Ch R = 1 ,9301.893,147.217500,147.217500,147.217500
XS GIS Cut Line= 6
 794545.13235719792711.914054807794848.358442656792519.351188486
795026.807281122792434.546045155795085.934214002792362.858999215
795157.097687811792289.157981515 795471.22704661791994.684649307
#Sta/Elev= 30
9408.462426.81849479.624 396.8279562.831358.56099657.924325.17159672.347321.6424
9718.685305.17879728.526300.8028    9752284.24849767.679278.5696 9797.85263.2214
9820.499249.12959831.824245.32639843.149243.33259864.942243.72039897.321241.6654
9965.549 240.40510004.57236.443410042.75 242.41310057.19246.543310069.56248.6504
10269.06250.405810282.92248.433110297.07250.970110310.64255.799910325.96263.1627
10338.36270.365210355.07272.162610420.05271.837610542.42279.147210591.68 279.533
#Mann= 3 , 0 , 0
9408.462    0.12       09408.462    0.12       010591.68    0.12       0
#XS Ineff= 2 , 0
       09935.759        10052.73       0
Bank Sta=9408.462,10591.68
Exp/Cntr=0.3,0.1

Type RM Length L Ch R = 1 ,9154.676,147.217600,147.217600,147.217600
XS GIS Cut Line= 6
794506.689290031792751.238031598794916.980680408792503.217923503
794980.643470988792500.228098252795074.536498645792554.738115948
795184.755048596792526.412544247795492.449788836792244.707307459
#Sta/Elev= 30
9405.149452.74589490.661417.27769593.345369.67839694.093332.82139712.222324.2414
9731.081320.95219771.248305.09779782.746298.91699794.244290.45879805.741284.7923
9817.239281.80499850.849265.13389872.607 250.195  9880.1246.7181 9903.71242.8465
9965.641240.699210003.08235.450410016.48236.313910039.96247.255810050.53249.5885
10070.74251.829210111.23253.145610153.61258.259610258.88257.982510284.23264.7283
 10316.6266.437610350.85265.834210392.57 260.26210459.06 269.21410594.78271.9963
#Mann= 3 , 0 , 0
9405.149  0.0654       09405.149  0.0654       010594.78  0.0654       0
#XS Ineff= 2 , 0
       09957.641                       0
Bank Sta=9405.149,10594.78
Exp/Cntr=0.3,0.1

Type RM Length L Ch R = 1 ,9007.458,147.217500,147.217500,147.217500
XS GIS Cut Line= 6
794672.911874235793072.998277809794932.528289236792824.367304739
795017.526667555792718.466183971795101.414723743792588.698435973
795292.007600939792457.573851426795505.397316333792234.773794354
#Sta/Elev= 30
9404.479341.64279459.958370.45999486.322381.27399499.504383.30699526.227382.2173
9567.235370.01639608.686354.13869695.658325.38749749.889309.01079783.635304.6472
9799.134298.48869815.833297.34149833.662293.4228 9854.24292.39789916.303282.4126
9931.746276.31999949.833264.80719963.885253.64819989.489237.68019998.524234.7783
10010.11234.531310044.57 244.67710134.74  257.6310239.07257.792410264.64264.5276
10304.43266.387310331.71265.775410373.35260.207310446.06269.339910595.41 272.176
#Mann= 3 , 0 , 0
9404.479    0.04       09404.479    0.04       010595.41    0.04       0
#XS Ineff= 2 , 0
       0                               0
Bank Sta=9404.479,10595.41
Exp/Cntr=0.3,0.1

Type RM Length L Ch R = 1 ,8860.241,147.217600,147.217600,147.217600
XS GIS Cut Line= 6
 794878.86767874793181.782989606794983.329374009793069.890030067
795090.227587395792924.695299054795149.017031426792821.501692109
795265.071346422792575.799382161795567.980913958792218.658115386
#Sta/Elev= 30
9403.514351.93829441.171 347.5619544.132313.99989600.935301.90449626.328298.6445
9700.414298.18859724.586 296.5689746.293297.77529771.704295.89919907.181270.3712
9918.222267.43459940.015253.28789961.557242.2064  9983.1236.317610004.64233.7469
10022.52236.171510037.16242.815710048.41245.297310128.02 252.80810176.55254.2144
10222.86264.020410246.05263.405510299.04257.243210344.74265.488310375.52268.3345
10417.69268.073710468.25270.792710522.61271.346610560.99269.3414 10596.5261.3606
#Mann= 3 , 0 , 0
9403.514    0.04       09403.514    0.04       0 10596.5    0.04       0
#XS Ineff= 2 , 0
       0                               0
Bank Sta=9403.514,10596.5
Exp/Cntr=0.3,0.1

Type RM Length L Ch R = 1 ,8713.023,147.217500,147.217500,147.217500
XS GIS Cut Line= 6
795014.083063577793254.320462053795109.240870314793147.039237779
795190.208236732793033.003647429795466.942633546792513.998063469
795551.207206813 792385.37484016795654.257100364792248.284600052
#Sta/Elev= 30
9401.518325.24149428.112329.02499453.933328.91099521.337321.49789571.245311.5645
 9609.99302.34899682.477282.92439740.343271.29419864.794267.17729906.781263.1913
 9931.98258.4359 9954.43246.67019977.105237.37499988.442234.03199999.784232.9448
10011.15233.0277 10067.8245.362110090.26244.631210122.82249.536410135.19250.0087
10269.22 250.33510295.67254.098910378.98256.373310415.99258.747810464.53255.3015
10484.47256.504810501.48249.572510514.16249.535710550.69253.289610598.51269.5805
#Mann= 3 , 0 , 0
9401.518    0.04       09401.518    0.04       010598.51    0.04       0
#XS Ineff= 2 , 0
       0                               0
Bank Sta=9401.518,10598.51
Exp/Cntr=0.3,0.1

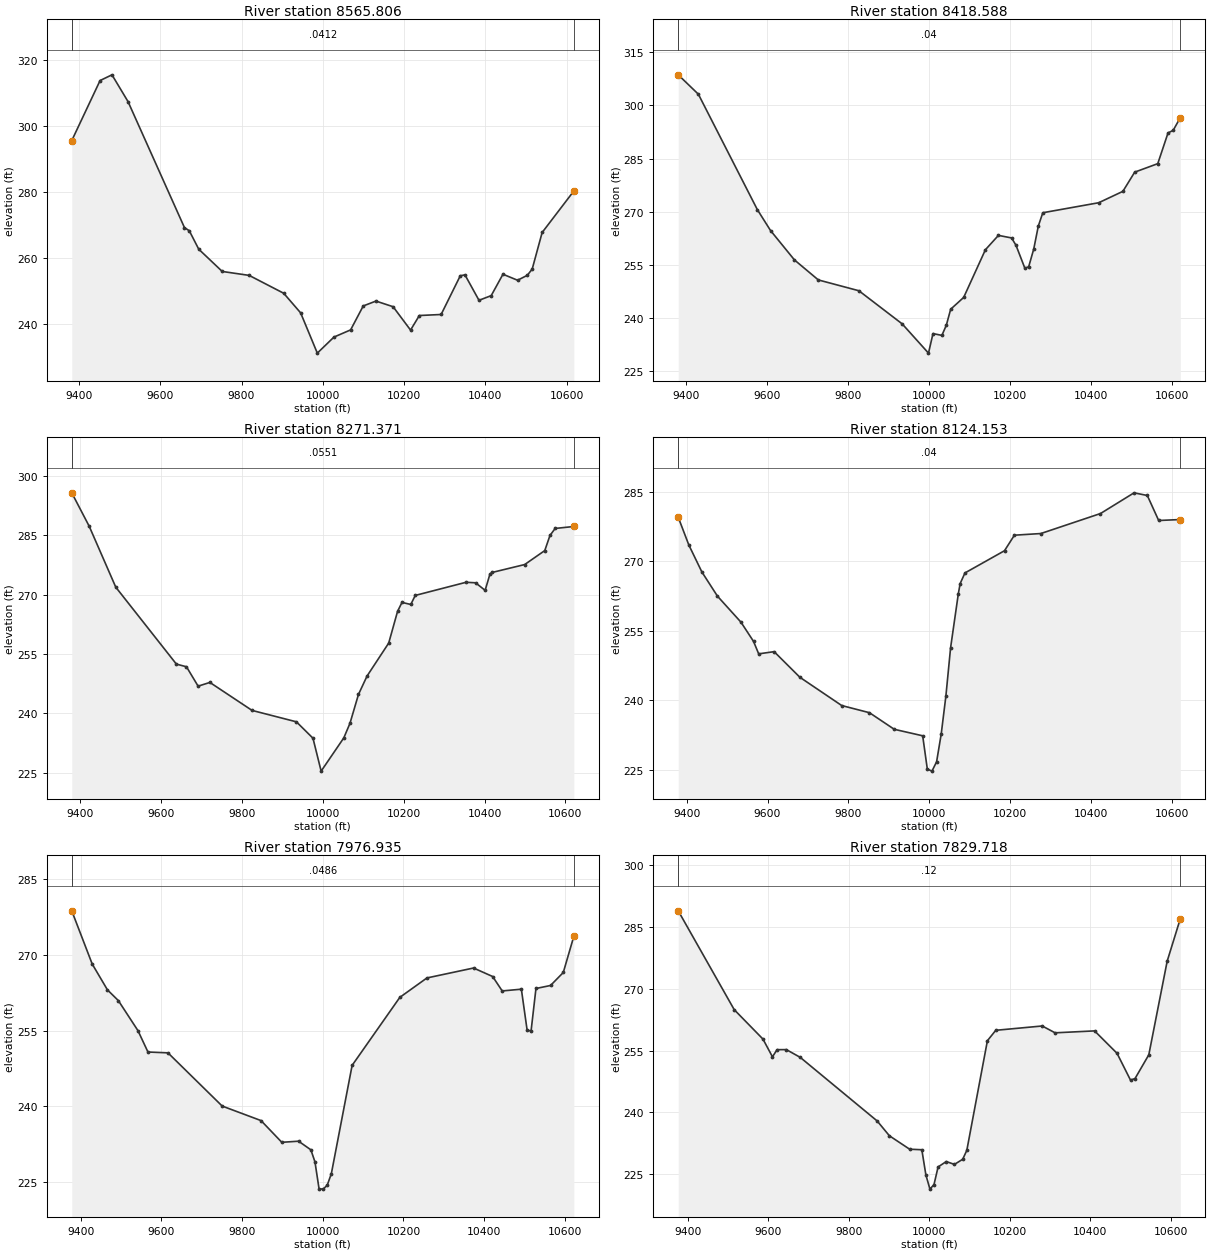
Type RM Length L Ch R = 1 ,8565.806,147.217600,147.217600,147.217600
XS GIS Cut Line= 6
795165.958541031 793335.55213271795286.682962893793205.365328219
795392.192389367793046.238485721 795443.75550923792924.629769257
795543.285116574792581.482208846795741.204852454792262.352836308
#Sta/Elev= 30
 9382.36295.5406 9452.02 313.7339481.277315.46059520.714307.36329659.527269.2103
9671.595268.20979694.749262.64859752.572255.90029818.807254.71019903.823249.2962
9945.447243.36189986.512231.163710027.45236.026510068.47238.204410099.48245.4536
10130.78246.929610172.96245.223110215.91 238.14210237.53242.555510291.11 242.867
10338.25254.595310349.76254.871910384.29247.162110414.37248.585810443.25255.0573
10479.23253.240710503.21254.7389 10515.2 256.62610539.69267.702210617.67280.2782
#Mann= 3 , 0 , 0
 9382.36  0.0412       0 9382.36  0.0412       010617.67  0.0412       0
#XS Ineff= 2 , 0
       0                10130.57       0
Bank Sta=9382.36,10617.67
Exp/Cntr=0.3,0.1

Type RM Length L Ch R = 1 ,8418.588,147.217500,147.217500,147.217500
XS GIS Cut Line= 6
795289.522462947793338.928873122 795426.42529052793196.593480259
795503.019690176793089.652323131795734.102909116792551.193816846
795821.247554913792404.637718205 795912.41843152792281.011740035
#Sta/Elev= 30
9380.011308.66789429.749303.18539575.463270.5367 9608.04264.63019666.984256.3353
9726.005250.67359826.204247.61479933.036 238.2559998.101229.977110009.18235.5034
10031.18234.995910042.15237.862510052.87242.387510085.04245.733510138.65259.2081
10170.82263.269810203.32 262.54610214.24260.462610236.09 253.99510245.57254.3986
10258.17259.474510269.31265.898310280.45269.6722 10418.5272.501610478.23275.7244
10507.36281.149710564.37283.553310589.68292.234910602.34292.966410620.04296.5518
#Mann= 3 , 0 , 0
9380.011    0.04       09380.011    0.04       010620.04    0.04       0
#XS Ineff= 2 , 0
       0                               0
Bank Sta=9380.011,10620.04
Exp/Cntr=0.3,0.1

Type RM Length L Ch R = 1 ,8271.371,147.217600,147.217600,147.217600
XS GIS Cut Line= 6
795372.098256208793365.208760016795589.628121544793173.436519023
795693.073374312793051.037142632795819.622083606792670.462062082
795912.183045616792510.708245515796034.071363111792349.012175535
#Sta/Elev= 30
9379.159295.71259422.213287.28429488.015271.88179637.897252.45479662.854251.7855
 9691.61246.88559720.725247.8293    9825240.76299934.732237.88099975.675233.7424
9995.869225.429110052.02233.8375 10067.2237.510910088.23 244.80510109.41249.4416
   10163257.771510184.86265.773310195.79 268.03710217.66267.515210228.59269.8015
10354.26273.119710377.85272.991610401.43271.084110413.22 275.14410418.29 275.592
10499.29277.600610548.96281.1284 10561.8 284.94610574.64286.714210620.85 287.212
#Mann= 3 , 0 , 0
9379.159  0.0551       09379.159  0.0551       010620.85  0.0551       0
#XS Ineff= 2 , 0
       0                               0
Bank Sta=9379.159,10620.85
Exp/Cntr=0.3,0.1

Type RM Length L Ch R = 1 ,8124.153,147.217500,147.217500,147.217500
XS GIS Cut Line= 6
795438.917221103793341.247060334 795711.36185065793125.801950484
795810.079636669793037.212490421796015.883499145792731.695012601
796124.842379265792605.697493487796283.072597292792444.286928067
#Sta/Elev= 30
 9379.09  279.529405.283273.53339437.527 267.7149476.087262.48789534.257256.8686
9565.329252.71819578.078250.03039616.325250.50169680.069244.96599783.488238.8685
9852.099237.32119913.437233.73899983.699232.33759995.198225.147410006.66224.7098
10018.14226.723510029.61232.745310041.09240.896110052.74251.343610071.93263.0288
10076.44265.211410088.28 267.499 10186.1272.296510210.56275.647610276.01276.0059
10423.52 280.324 10506.5284.794410539.33284.220210567.44278.819910620.94279.0278
#Mann= 3 , 0 , 0
 9379.09    0.04       0 9379.09    0.04       010620.94    0.04       0
#XS Ineff= 2 , 0
       0                               0
Bank Sta=9379.09,10620.94
Exp/Cntr=0.3,0.1

Type RM Length L Ch R = 1 ,7976.935,147.217600,147.217600,147.217600
XS GIS Cut Line= 6
 795444.77729168793345.192304724795812.257502476793082.508016356
795887.976320316793050.356337266796145.472779335792979.493864073
796310.804591443792889.329531822796522.904311999792750.377622581
#Sta/Elev= 30
9377.732278.70289428.401268.17419466.192263.05869493.153260.9435 9541.77254.9969
9566.571 250.7639616.173250.59889750.588 240.0669846.876237.19119898.348232.8955
9939.966233.11449970.431231.40499980.559229.02019990.686223.705710000.82223.6286
10010.97224.407910021.11226.660610072.67248.120410190.95261.579910258.12265.4201
10373.65267.3852   10421265.703710444.68262.848310492.19263.195510506.56255.0312
 10516.3254.965310528.36263.332410564.52  263.9310596.09266.499310622.27273.6724
#Mann= 3 , 0 , 0
9377.732  0.0486       09377.732  0.0486       010622.27  0.0486       0
#XS Ineff= 2 , 0
       0                               0
Bank Sta=9377.732,10622.27
Exp/Cntr=0.3,0.1

Type RM Length L Ch R = 1 ,7829.718,253.055700,253.055700,253.055700
XS GIS Cut Line= 6
795400.726707742793421.171693714795587.070595356793295.567513286
 795720.77489889793226.757691743796190.457263919793128.621803826
796347.019899863793066.658912519796543.569840485792964.142688965
#Sta/Elev= 30
9376.741288.9707 9515.72264.94889587.155257.78869610.635253.49169622.161255.2229
9645.212255.23819679.542253.36059870.664237.89219900.969234.29859951.303231.0298
9981.503230.9046 9991.57224.788610001.63221.329910011.74222.440710021.87226.7178
10042.15228.031510062.53227.339510082.98228.5895 10093.2230.755510144.32257.4028
10165.06259.931910280.43260.982210312.33259.320110410.41259.789310466.16254.3411
10499.61247.821510510.81248.203910545.03253.978710590.66276.741710623.24287.0503
#Mann= 3 , 0 , 0
9376.741    0.12       09376.741    0.12       010623.24    0.12       0
#XS Ineff= 2 , 0
       0                               0
Bank Sta=9376.741,10623.24
Exp/Cntr=0.3,0.1

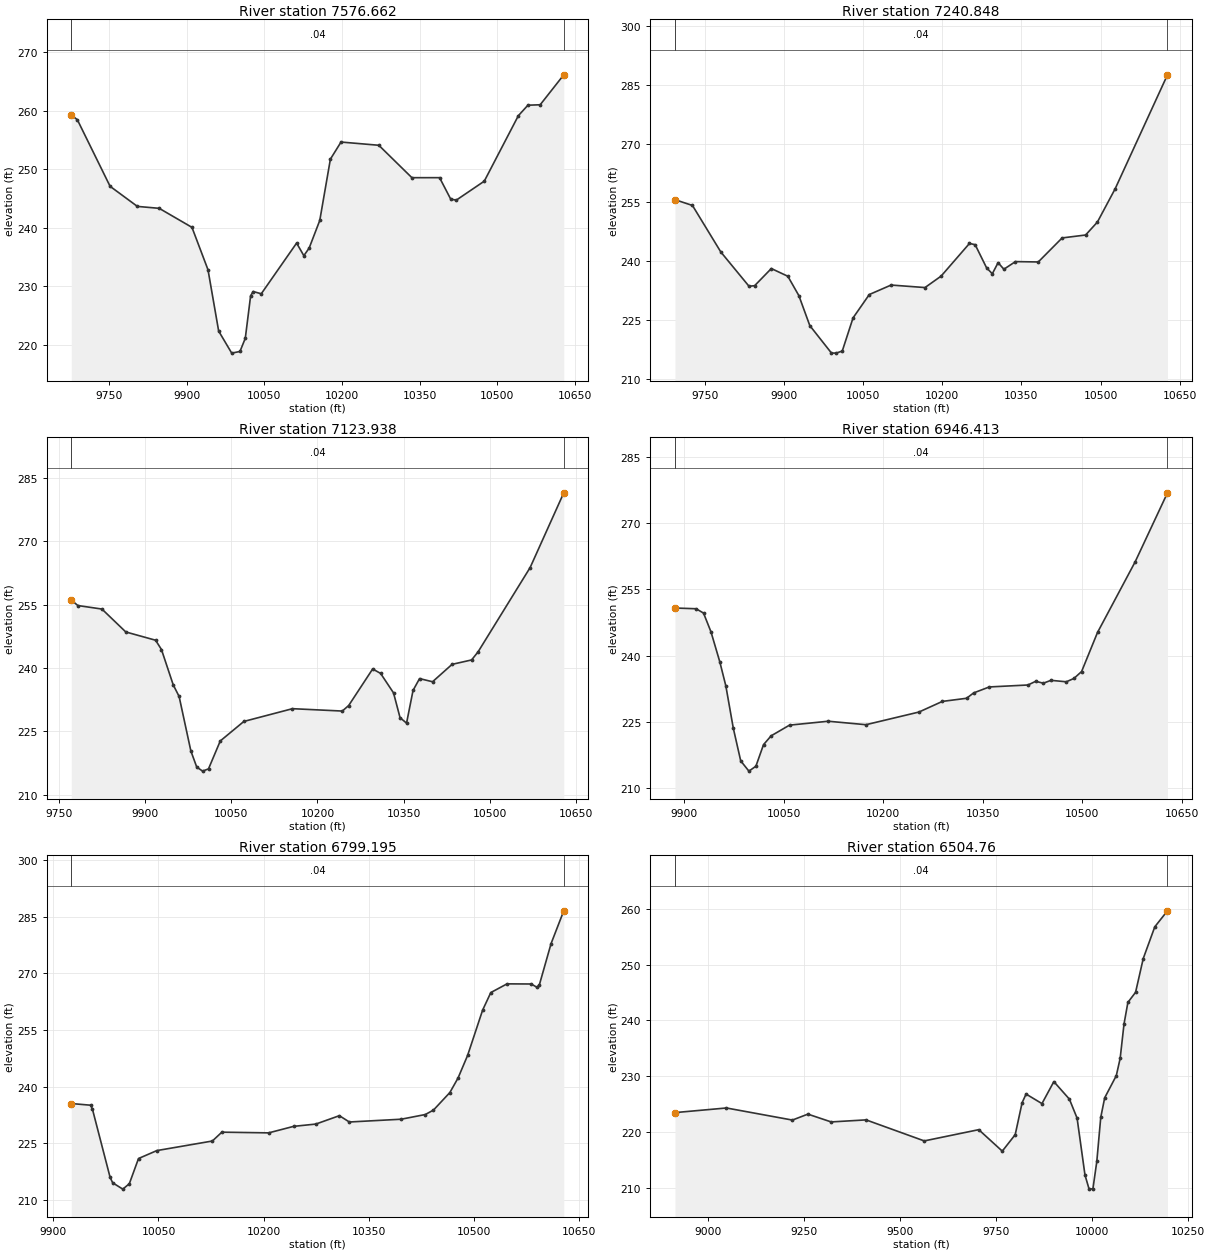
Type RM Length L Ch R = 1 ,7576.662,335.814500,335.814500,335.814500
XS GIS Cut Line= 6
795643.926468372793498.941439167795870.488968402793422.118522525
796171.138312399793348.968325049796210.236687243793336.015575156
796415.182365417793255.899214923796544.672915667 793195.80506441
#Sta/Elev= 30
9676.384 259.2329688.077258.43379751.432247.06299804.228243.63219846.465243.3028
9909.821240.0549 9940.87232.80749961.477222.34759986.717218.581910002.69218.8667
10012.99221.1127 10023.3228.365210028.25 229.099 10043.9228.715310112.29237.3717
10126.23235.219510136.51236.510510157.07241.232710177.62251.701910198.18254.6209
10271.31254.068410335.27248.535510388.82248.538310410.44244.864710421.25244.7059
10475.31247.939810541.23259.117910559.72260.910710583.47 260.98410629.07266.0959
#Mann= 3 , 0 , 0
9676.384    0.04       09676.384    0.04       010629.07    0.04       0
#XS Ineff= 2 , 0
       0                               0
Bank Sta=9676.384,10629.07
Exp/Cntr=0.3,0.1

Type RM Length L Ch R = 1 ,7240.848,116.910100,116.910100,116.910100
XS GIS Cut Line= 6
795844.240907854793755.877517532795998.473010147 793696.64848858
796237.014129969793636.003193493796346.227166829793599.246373131
796488.794461842  793537.6846483796713.183949389 793425.47019347
#Sta/Elev= 30
9693.897255.71289726.987254.23659780.732 242.3459834.077233.59789844.746233.7337
9876.377238.1196  9907.7236.14329928.582 231.1939949.284223.54059990.278216.5287
    9999216.506110010.76217.034410031.22225.513910061.99231.4772 10103.3233.9014
10167.51233.259210198.05236.186110251.73244.528510262.53244.218210284.14238.3134
10295.03236.7813   10306239.620410316.96237.9445 10338.9239.892210382.12239.7993
 10427.3245.940210471.75246.687610494.07249.982910527.78258.503110626.86287.6155
#Mann= 3 , 0 , 0
9693.897    0.04       09693.897    0.04       010626.86    0.04       0
#XS Ineff= 2 , 0
       09895.996                       0
Bank Sta=9693.897,10626.86
Exp/Cntr=0.3,0.1

Type RM Length L Ch R = 1 ,7123.938,177.525000,177.525000,177.525000
XS GIS Cut Line= 6
795934.216064049793834.649541436796071.048158169793793.923774588
796221.432825466793760.193288276 796305.46908258793732.765340594
796451.352648021793665.854991629796726.692222666793519.144411468
#Sta/Elev= 30
9771.281256.09019782.644254.77129824.654253.93769866.223248.51149918.123246.5533
9928.365244.35119948.847 235.9789959.088233.23939979.571220.32519989.812 216.506
10000.05215.544610010.31216.078610030.82222.692510071.92227.315410156.63230.3366
 10243.4229.774610254.52231.090210296.27239.742410310.12238.689810332.64234.0733
10343.98228.211910355.31226.910110366.64234.668610377.97237.465810400.63236.7177
10434.62240.838510468.62241.881810479.95243.8054 10570.6263.768910629.17281.4701
#Mann= 3 , 0 , 0
9771.281    0.04       09771.281    0.04       010629.17    0.04       0
#XS Ineff= 2 , 0
       0                10079.58       0
Bank Sta=9771.281,10629.17
Exp/Cntr=0.3,0.1

Type RM Length L Ch R = 1 ,6946.413,147.217500,147.217500,147.217500
XS GIS Cut Line= 6
796106.090951273 793994.24815081796130.112914417793983.531005769
796196.566642121793950.107157974796277.389889546 793904.68908712
796541.012343515793740.734534505796747.190103171793622.667350058
#Sta/Elev= 30
9886.571250.80819918.346250.64029929.539249.65889940.733245.41719954.117238.5784
 9963.12233.17339974.314223.61989985.508216.20399997.846213.881110008.36214.9901
10019.84219.874210031.32221.875710058.97224.290910117.25225.176110174.06224.3915
 10253.8227.255110289.13229.665610325.54230.372210336.23231.590410359.79232.9385
10418.06233.381310429.59234.216610441.11233.785310452.63234.436110475.68234.1068
 10487.2234.863410498.73236.4298 10522.7245.275510579.39261.270110628.01276.8843
#Mann= 3 , 0 , 0
9886.571    0.04       09886.571    0.04       010628.01    0.04       0
#XS Ineff= 2 , 0
       0                10071.65       0
Bank Sta=9886.571,10628.01
Exp/Cntr=0.3,0.1

Type RM Length L Ch R = 1 ,6799.195,294.435100,294.435100,294.435100
XS GIS Cut Line= 6
796243.237078227794114.022435038796296.256963054794060.522872586
796394.169462559793947.560840298796481.324329518793868.899768773
796609.861780114793779.340445436796785.246485856793676.018313944
#Sta/Elev= 30
9925.631235.57649953.259235.13379955.809234.08589980.978216.06389984.695214.5924
9999.141212.922210008.45214.357610021.55221.022410047.72223.124610126.93225.6581
10140.45227.998710207.28227.813810242.96229.539110274.54230.141810308.12232.3618
10322.35230.691110396.33231.426610430.71 232.66710442.39233.845410465.77238.4861
10477.45242.329310491.07248.302610512.51260.3009 10524.2264.950610547.34267.2539
10581.91267.218110590.06266.340110593.43266.970110610.19277.915410628.28286.5843
#Mann= 3 , 0 , 0
9925.631    0.04       09925.631    0.04       010628.28    0.04       0
#XS Ineff= 2 , 0
       0                               0
Bank Sta=9925.631,10628.28
Exp/Cntr=0.3,0.1

Type RM Length L Ch R = 1 , 6504.76,163.456100,163.456100,163.456100
XS GIS Cut Line= 6
795422.410278052794380.460861623796103.749880612794283.022460595
796277.656241149794250.363293588796421.940018058794214.434863374
796585.047625214794238.999322981796687.679926068794232.475320414
#Sta/Elev= 30
8913.286223.49979047.224224.32839218.954222.16139259.361223.22599319.971221.8296
9410.887222.19499562.413218.42699704.293220.44249765.605216.59489799.283219.5481
9817.196225.25749827.548226.82329868.956225.11279899.906229.05039940.371225.9132
9960.429222.50749980.977212.32089991.251209.897410001.53209.790410011.79214.7498
10022.04222.6422 10032.3226.145610062.55230.120410072.61 233.21710082.67239.3834
10092.73 243.24310112.73245.048310132.74251.106210162.82256.7867 10195.8259.6477
#Mann= 3 , 0 , 0
8913.286    0.04       08913.286    0.04       0 10195.8    0.04       0
#XS Ineff= 2 , 0
       09896.965                       0
Bank Sta=8913.286,10195.8
Exp/Cntr=0.3,0.1