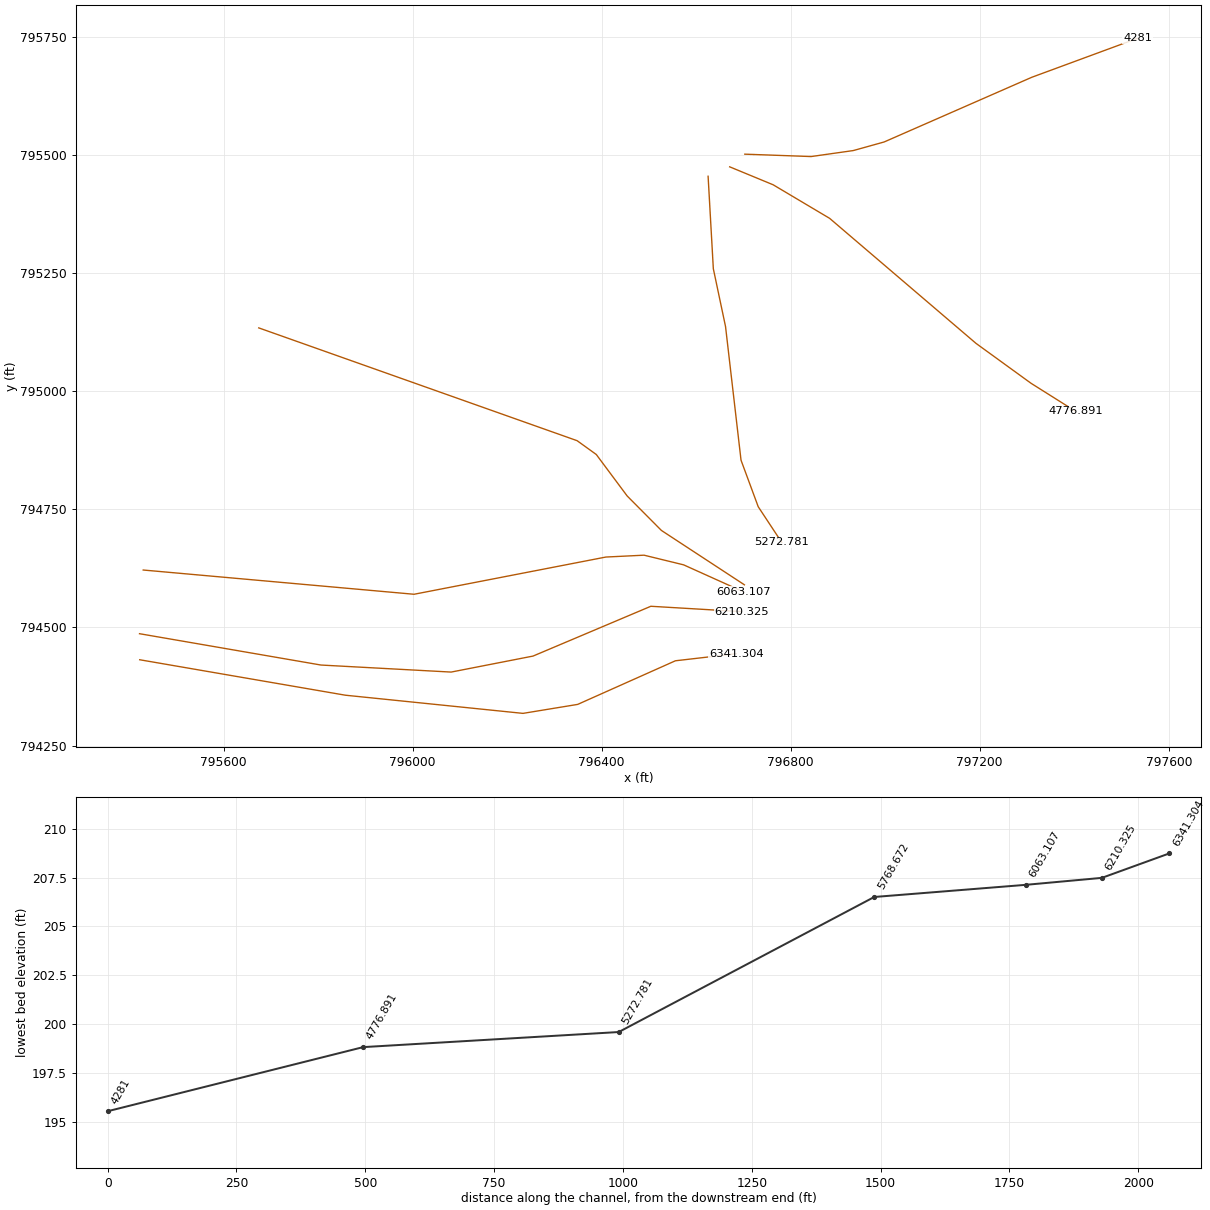
HEC-RAS study 17588_ras.prj: 17588

--- 17588_ras.g01 (geometry) --- (continued)

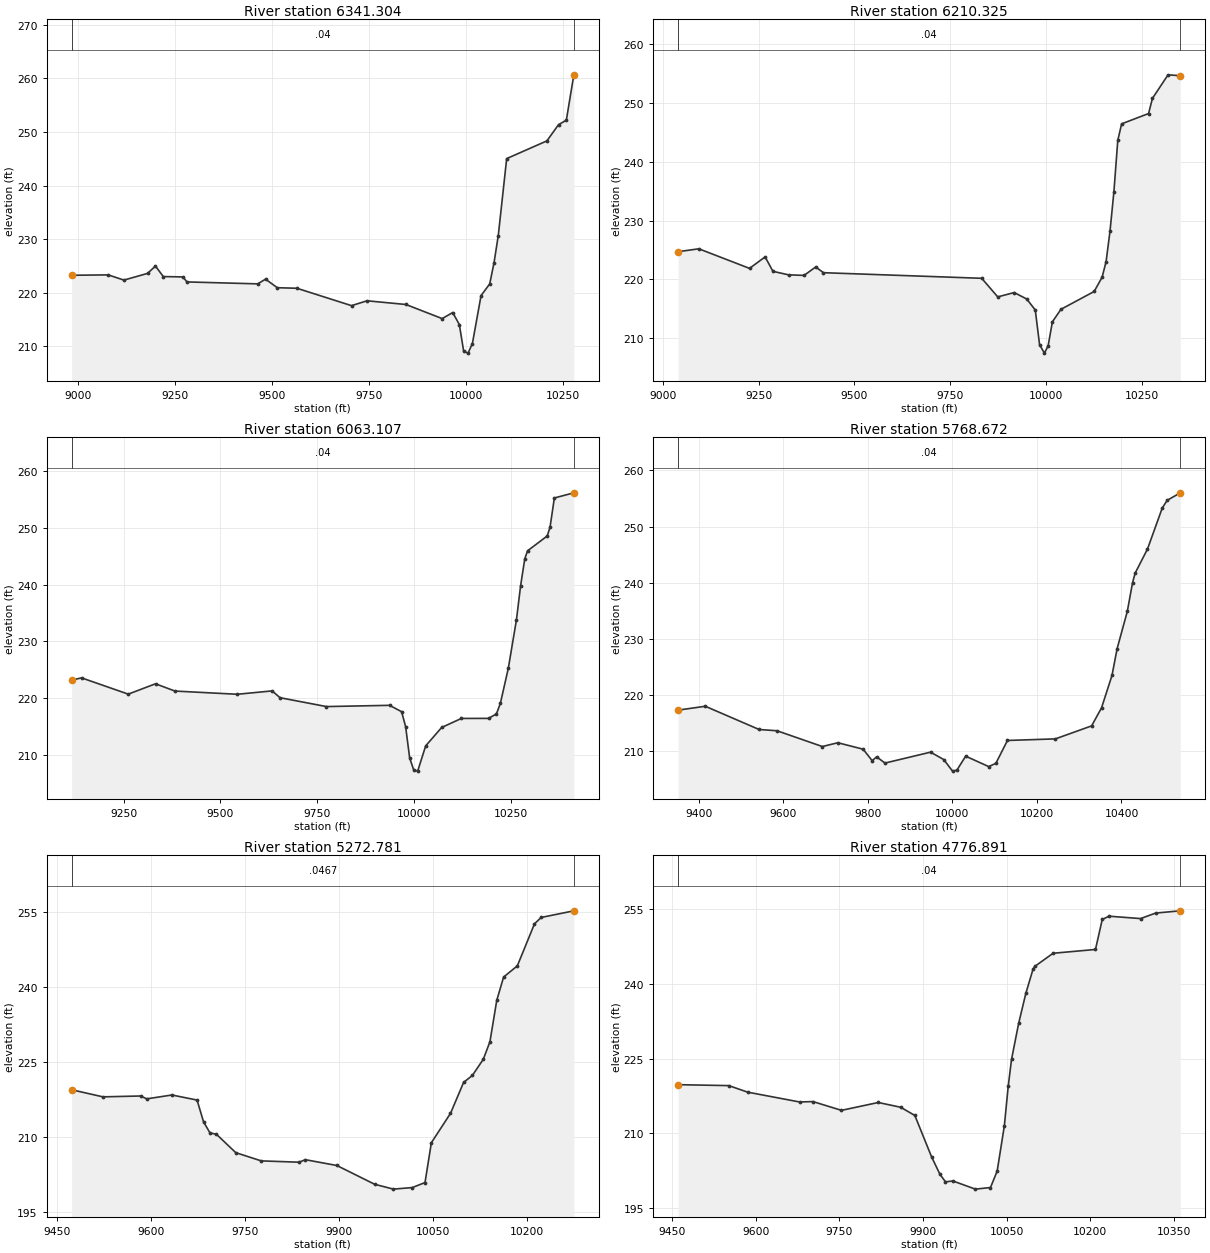
Type RM Length L Ch R = 1 ,6341.304,130.979000,130.979000,130.979000
XS GIS Cut Line= 6
 795422.21997091794431.613156857795857.506629723794356.572035679
796233.328294544794318.123987623796349.120601445794337.135389379
 796555.91664958794429.430189087796684.325107184794444.263130615
#Sta/Elev= 30
8982.896223.26069077.045223.33439117.635222.3631 9178.52223.60929198.815224.9837
 9219.11223.01869269.848222.95559279.995222.02149462.435221.65839482.615222.5375
9512.885 220.9399563.335220.83969704.129217.59529744.278218.50129844.409217.8083
9937.815 215.1769964.933216.3087 9982.05214.0665 9993.27209.065510004.49208.7341
10015.69210.521510038.01219.469710060.34221.6518 10071.5225.620610082.41230.6785
10104.03245.033410207.67 248.33710237.77251.3696 10257.8252.196210277.13260.6648
#Mann= 3 , 0 , 0
8982.896    0.04       08982.896    0.04       010277.13    0.04       0
#XS Ineff= 2 , 0
       09959.009                       0
Bank Sta=8982.896,10277.13
Exp/Cntr=0.3,0.1

Type RM Length L Ch R = 1 ,6210.325,147.217600,147.217600,147.217600
XS GIS Cut Line= 6
795421.795986865794486.733228798795805.801793977794420.423014308
 796081.26772879794405.532047534796254.625153312794439.396908713
796503.958266263794544.794934114796695.855916843794533.455902298
#Sta/Elev= 30
 9040.48224.70599094.536225.19499226.617221.87099267.257223.82419287.577221.3701
9328.217220.77529368.701220.68049399.043222.10759419.271221.13859831.759220.1869
9873.524217.03159916.477217.76839949.038216.66979971.356214.80399982.516208.9217
9995.173207.483610004.84 208.72110015.97212.803710038.22214.922610124.78217.9489
10145.58220.3777 10155.9223.026310166.06228.165810176.22234.856910186.38243.6039
10196.41246.411110266.64248.161310276.73250.739610317.38254.732410349.32254.5841
#Mann= 3 , 0 , 0
 9040.48    0.04       0 9040.48    0.04       010349.32    0.04       0
#XS Ineff= 2 , 0
       09945.072        10069.35       0
Bank Sta=9040.48,10349.32
Exp/Cntr=0.3,0.1

Type RM Length L Ch R = 1 ,6063.107,294.435100,294.435100,294.435100
XS GIS Cut Line= 6
795429.584531367794621.519887924796002.753721744 794570.20244582
796408.805527687794648.982375279796489.569868743794652.910372123
796573.311754167794632.461211726796700.335549414794575.188515082
#Sta/Elev= 30
9115.491223.1684 9141.05223.56859261.728220.69989332.124222.52349382.406221.2437
9543.486220.67599633.661 221.2719653.662220.07329773.896218.50639936.924218.7276
 9968.02217.60029978.385214.9528 9988.75209.46689999.115207.352710009.48207.1283
 10030.2211.583310071.51214.826810122.39216.414710192.66216.425410212.95217.2187
10223.09219.053810243.76225.292910264.78233.850310275.37239.780410286.17244.5418
 10293.3245.956510344.25 248.58310351.53250.143810362.63 255.27810412.95256.1845
#Mann= 3 , 0 , 0
9115.491    0.04       09115.491    0.04       010412.95    0.04       0
#XS Ineff= 2 , 0
       09935.645                       0
Bank Sta=9115.491,10412.95
Exp/Cntr=0.3,0.1

Type RM Length L Ch R = 1 ,5768.672,495.890700,495.890700,495.890700
XS GIS Cut Line= 6
795674.106869308795133.953761067796347.866087937 794895.23587094
796388.446512267794866.013872051796453.939683458794778.080336446
796526.269538329794705.290299083796701.949747212794590.226509893
#Sta/Elev= 30
9351.076217.36079415.342218.04789542.608213.9164 9585.16213.68589692.282210.8835
9728.915211.55689788.692210.41029810.116208.37339820.828 209.041 9840.48207.9401
9948.326209.88189979.536208.5634 10000.3206.506310010.67206.686410031.37209.1684
10085.82 207.31810102.79 207.88610130.25211.961610243.71212.244210329.37214.5575
10352.84217.767910377.53223.524110389.77228.313110413.79234.923310426.15240.0132
10432.37241.735810461.52 246.01910496.51 253.31910508.06254.683410539.18256.0192
#Mann= 3 , 0 , 0
9351.076    0.04       09351.076    0.04       010539.18    0.04       0
#XS Ineff= 2 , 0
       09964.702                       0
Bank Sta=9351.076,10539.18
Exp/Cntr=0.3,0.1

Type RM Length L Ch R = 1 ,5272.781,495.890700,495.890700,495.890700
XS GIS Cut Line= 6
796625.105944479795454.842307192796636.182898747795259.071676915
 796661.99098184795136.841906496796694.802819474794853.910287678
796731.206110335794755.415672403796781.057606935794679.832139563
#Sta/Elev= 30
9473.059219.44839522.981218.02959583.077218.20139593.093217.63089633.157218.4009
9673.348217.38849683.676213.04569694.003 210.8269704.331210.55549735.158206.8863
9775.747205.24449836.268204.97899846.329205.48039896.632 204.3219956.879200.5752
9986.982199.6024 10017.1199.916810037.39200.914110047.56208.875410078.09214.7281
10099.02 220.90910113.12222.320810130.48225.533910141.06229.0212   10152237.3117
10162.94241.957610184.84244.189210212.24252.584410222.88253.855210275.08255.1792
#Mann= 3 , 0 , 0
9473.059  0.0467       09473.059  0.0467       010275.08  0.0467       0
#XS Ineff= 2 , 0
       0                               0
Bank Sta=9473.059,10275.08
Exp/Cntr=0.3,0.1

Type RM Length L Ch R = 1 ,4776.891,495.890700,495.890700,495.890700
XS GIS Cut Line= 6
796670.790365912795474.804887272796762.820522526795436.793559026
796882.309180473795365.770156716797192.039219831795101.214724288
 797308.67964743795016.633421223797402.817486343794957.401047134
#Sta/Elev= 30
9460.365219.76169551.396219.57329585.177218.26299678.342216.29789702.564216.3721
9753.634214.61529819.678216.19149859.911215.23739885.367 213.5939915.383205.3018
 9930.39201.80899940.377200.29479953.788200.46169994.021198.831610021.18199.1533
10033.18202.455110046.06211.518110052.95 219.39710058.93224.8281 10071.8 232.088
10084.67238.078910097.54242.900710100.59243.452810133.56246.094410209.63246.8543
10221.83252.868110234.02253.521610290.63253.044110317.72 254.15110361.94254.5973
#Mann= 3 , 0 , 0
9460.365    0.04       09460.365    0.04       010361.94    0.04       0
#XS Ineff= 2 , 0
       0                               0
Bank Sta=9460.365,10361.94
Exp/Cntr=0.3,0.1

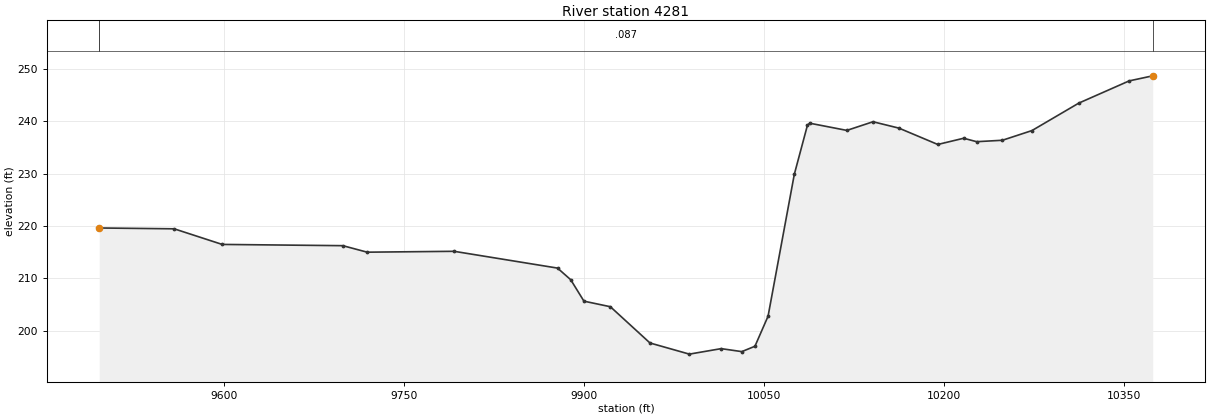
Type RM Length L Ch R = 1 ,    4281,0.000000,0.000000,0.000000
XS GIS Cut Line= 6
 796702.77267914795501.620826825796843.087434656795496.554950055
796932.362378224795509.230235341  796997.6498485795527.411624119
797310.155035721795664.334610482797533.758916647795746.745855081
#Sta/Elev= 30
9495.555219.64599558.056219.48579598.067216.50479698.656216.26569718.943215.0239
9791.432215.18999877.653211.98459888.667209.7584 9899.68205.66989921.708204.6054
9954.748197.68049987.572195.553610014.09196.6022 10031.3196.033310042.24197.0576
10053.19202.799710075.08229.909910086.02239.273710087.89239.657410118.86238.2807
10140.68239.932510162.27238.717610194.67235.594610216.26236.783110227.06236.1251
10248.55236.397610273.19238.248710312.23243.491710354.22247.734310373.89248.7039
#Mann= 3 , 0 , 0
9495.555   0.087       09495.555   0.087       010373.89   0.087       0
#XS Ineff= 2 , 0
       0                               0
Bank Sta=9495.555,10373.89
Exp/Cntr=0.3,0.1